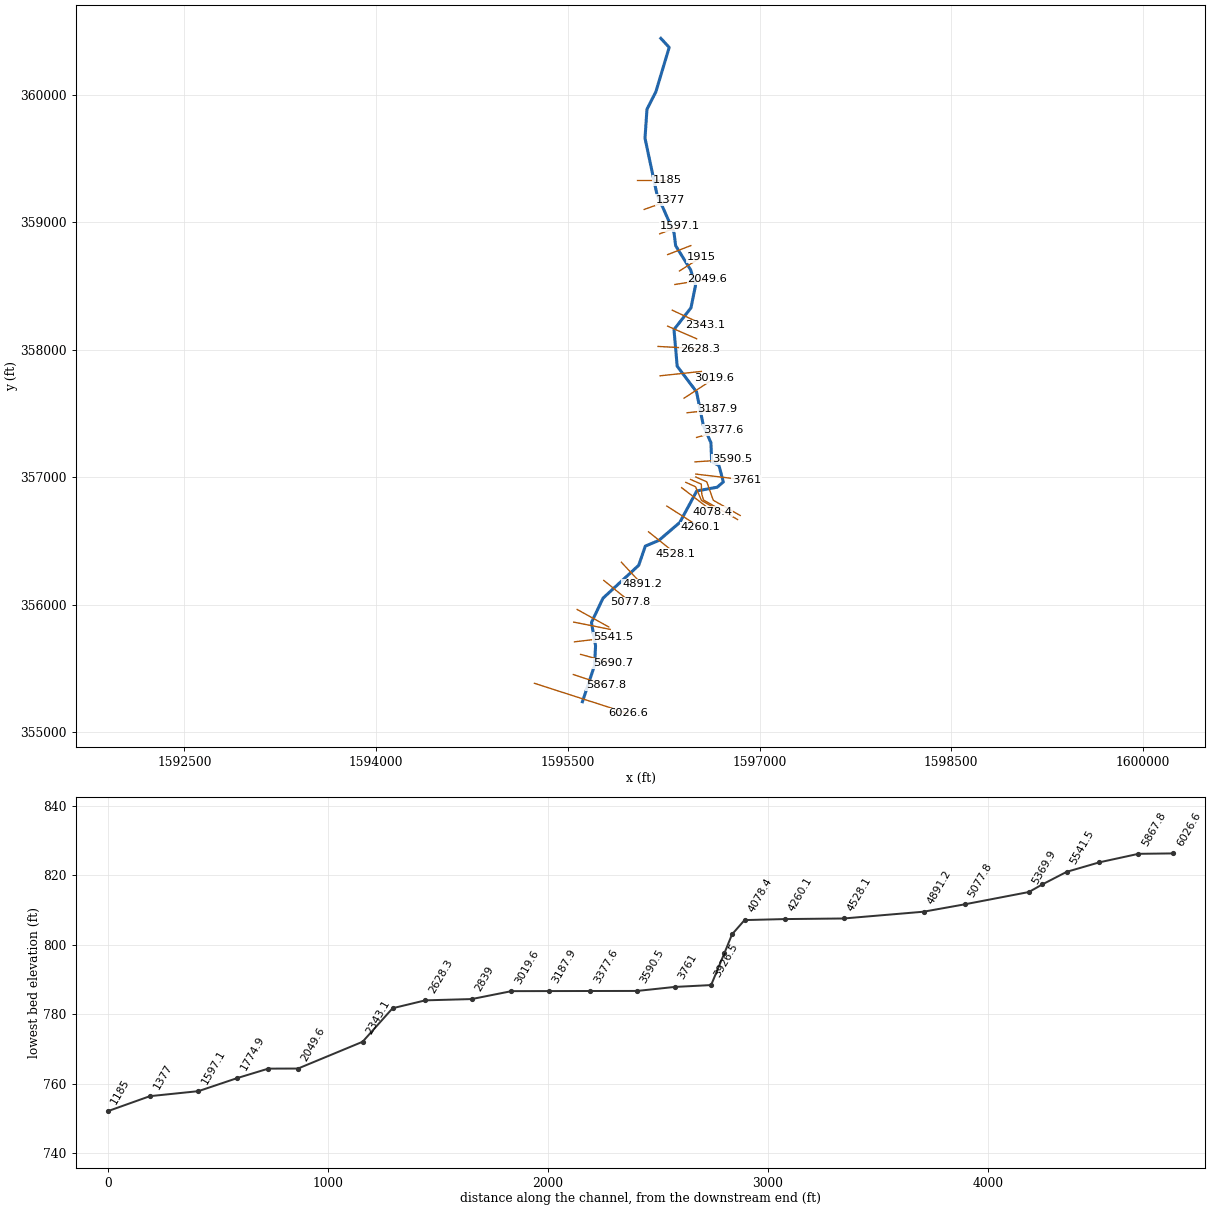
--- OPENFK.prj (project) ---

Proj Title=OPENFK
Current Plan=p01
Default Exp/Contr=0,0
English Units
Geom File=g01
Flow File=f01
Plan File=p01
BEGIN DESCRIPTION:
END DESCRIPTION:
DSS Export Rating Curves= 0
DSS Export Rating Curve Sorted= 0
DSS Export Volume Flow Curves= 0
DXF OffsetX= 0
DXF OffsetY= 0
DXF ScaleX= 0
DXF ScaleY= 0

--- OPENFK.p01 (plan) ---

Plan Title=Floodplain
Program Version=4.00
Geom File=g01
Flow File=f01
K Sum by GR=0
Std Step Tol=0.01
Critical Tol=0.01
Num of Std Step Trials=20
Max Error Tol=0.3
Flow Tol Ratio=0.001
Split Flow NTrial=30
Split Flow Tol=0.02
Split Flow Ratio=0.02
Log Output Level=0
Friction Slope Method=1
Unsteady Friction Slope Method=2
Unsteady Bridges Friction Slope Method=1
Global Log Level=0
CheckData=False
Run HTab=0
Run UNet=0
Run PostProcess=0
UNET Theta=0
UNET Theta Warmup=0
UNET ZTol=0
UNET ZSATol=0
UNET MxIter=0
UNET MaxInSteps=0
UNET DtIC=0
UNET DtMin=0
UNET MaxCRTS=0
UNET WFStab=0
UNET SFStab=0
UNET WFX=0
UNET SFX=0
UNET DSS MLevel=0
UNET DZMax Abort=0
UNET Convert EG Bridges=0
UNET Use Existing IB Tables=0
UNET Froude Limit=0
UNET Froude Power=0
Write IC File=0
Echo Input=False
Echo Output=False
Write Detailed=0

--- OPENFK.f01 (steady flow) ---

Flow Title=NFF Regression Equation
Program Version=4.00
Number of Profiles=1
Profile Names=P100yr
River Rch & RM=OPENFK,Main      ,6026.6
     355
River Rch & RM=OPENFK,Main      ,5077.8
376.1227
River Rch & RM=OPENFK,Main      ,3590.5
417.2420
River Rch & RM=OPENFK,Main      ,1185
449.6820
Boundary for River Rch & Prof#=OPENFK,Main      ,1
Up Type=0
Dn Type=3
Dn Slope=0.016816

--- OPENFK.g01 (geometry) ---

Geom Title=Geometry
Program Version=4.00

River Reach=OPENFK          ,Main
Reach XY= 30
     1595614.256      355240.534     1595709.325       355525.74
     1595716.918      355678.551     1595684.948      355862.137
     1595775.142      356052.275     1596054.576        356310.4
     1596106.334      356460.859     1596212.257      356505.395
     1596375.956      356646.224     1596508.877      356893.267
     1596668.544      356922.519     1596716.499      356963.869
     1596682.892      357091.583     1596625.116      357124.082
     1596619.698      357271.632     1596560.341      357406.033
     1596507.138      357670.016     1596355.493      357871.562
     1596330.552      358158.608     1596463.598      358329.339
     1596499.113      358504.874     1596460.823      358627.059
     1596343.474      358816.151     1596330.836      358918.175
     1596196.675      359221.181     1596103.723      359659.041
     1596119.208      359886.158     1596188.607      360022.514
     1596292.954      360370.869     1596227.665      360442.039

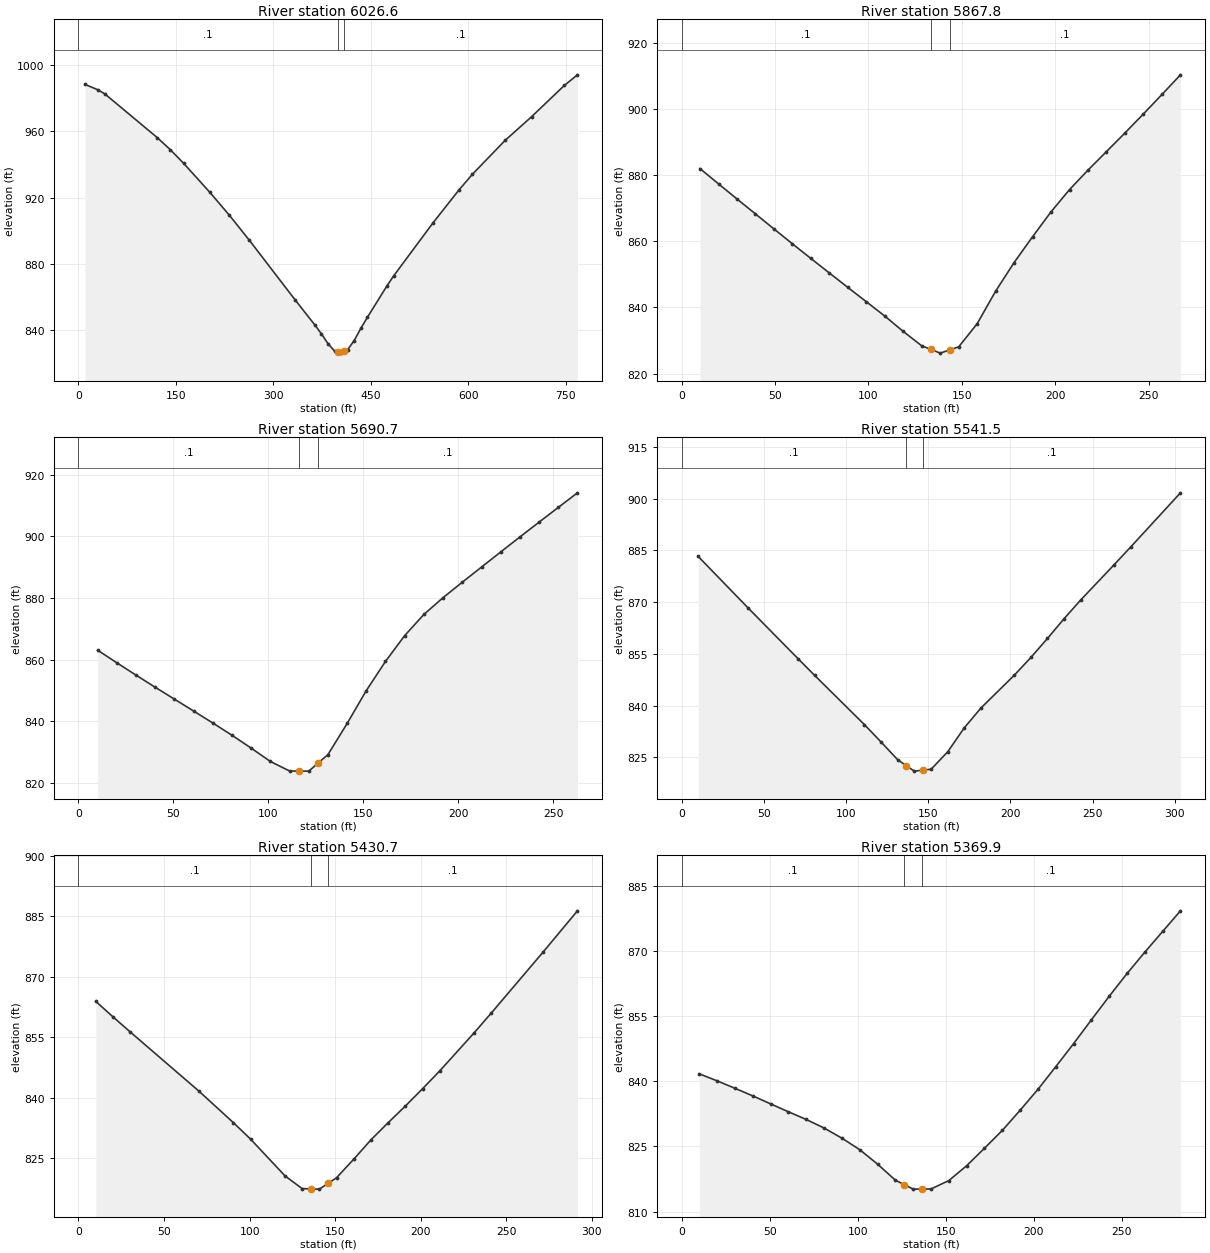
Type RM Length L Ch R = 1 ,6026.6  ,159.1,158.8,158.4
XS GIS Cut Line= 2
     1595238.651      355385.059     1595969.804        355149.3
#Sta/Elev= 30
    10.1  988.32    30.3     985    40.4  982.67   121.3  956.24   141.5  948.93
   161.7  940.83   202.2   923.3   232.5  909.34   262.8   894.5   333.6  858.37
   363.9  843.29     374  837.94   384.1  832.06   394.2  827.58   399.3  826.93
   404.3   826.3   409.3  827.31   414.4  828.34   424.5  833.91   434.7  841.21
   444.8   847.9   475.1  866.95   485.2  872.86   545.8  904.83   586.3  924.94
   606.5  934.15     657  954.63   697.5  968.82     748  987.69   768.2  994.11
#Mann= 3 , 0 , 0
       0      .1       0   399.3    .045       0   409.3      .1       0
Bank Sta=399.3,409.3
XS Rating Curve= 0 ,0
Exp/Cntr=0.3,0.1

Type RM Length L Ch R = 1 ,5867.8  ,176.1,177.1,178.1
XS GIS Cut Line= 2
      1595543.05      355453.698     1595796.715      355370.137
#Sta/Elev= 29
     9.9  881.97    19.8  877.37    29.7  872.79    39.6  868.26    49.5  863.73
    59.3  859.26    69.2  854.83    79.1  850.43      89  846.07    98.9  841.74
   108.8  837.39   118.7  832.74   128.6  828.39   133.5   827.3   138.5  826.18
   143.5  827.14   148.4  828.09   158.3   835.1   168.2  844.96     178  853.53
   187.9  861.35   197.8   868.9   207.7  875.62   217.6  881.52   227.5  887.12
   237.4  892.76   247.3  898.52   257.2  904.39   267.1  910.33
#Mann= 3 , 0 , 0
       0      .1       0   133.5    .045       0   143.5      .1       0
Bank Sta=133.5,143.5
XS Rating Curve= 0 ,0
Exp/Cntr=0.3,0.1

Type RM Length L Ch R = 1 ,5690.7  ,141.5,149.2,157
XS GIS Cut Line= 2
     1595599.751      355611.865     1595853.416      355543.227
#Sta/Elev= 28
    10.1  863.02    20.2  858.94    30.3  854.93    40.4  850.99    50.5  847.14
    60.6  843.28    70.8  839.35    80.9  835.38      91  831.19   101.1  826.87
   111.2  823.78   116.3  823.76   121.3  823.74   126.3   826.4   131.4  829.12
   141.5  839.22   151.6  849.92   161.7  859.38   171.8  867.76   181.9  874.63
     192  880.08   202.1  885.09   212.3  890.04   222.4  894.95   232.5  899.82
   242.6  904.63   252.7   909.4   262.8  914.15
#Mann= 3 , 0 , 0
       0      .1       0   116.3    .045       0   126.3      .1       0
Bank Sta=116.3,126.3
XS Rating Curve= 0 ,0
Exp/Cntr=0.3,0.1

Type RM Length L Ch R = 1 ,5541.5  ,117.2,110.8,104.4
XS GIS Cut Line= 2
     1595552.002      355710.347     1595853.416      355746.159
#Sta/Elev= 22
    10.1  883.26    40.5   868.3    70.8  853.63    80.9  848.79   111.3  834.45
   121.4  829.43   131.5  824.29   136.6  822.62   141.6  820.99   146.6  821.26
   151.8  821.53   161.9  826.58     172  833.55   182.1  839.27   202.4  848.79
   212.5  853.94   222.6  859.46   232.7  865.18   242.8  870.61   263.1  880.81
   273.2  885.97   303.5  901.68
#Mann= 3 , 0 , 0
       0      .1       0   136.6    .045       0   146.6      .1       0
Bank Sta=136.6,146.6
XS Rating Curve= 0 ,0
Exp/Cntr=0.3,0.1

Type RM Length L Ch R = 1 ,5430.7  ,67,60.8,54.6
XS GIS Cut Line= 2
     1595546.002      355864.778     1595832.021      355807.899
#Sta/Elev= 22
    10.1  863.91    20.1  860.09    30.2  856.34    70.4  841.65    90.5  833.85
   100.6  829.74   120.7  820.65   130.7  817.49   135.8  817.42   140.8  817.36
   145.8  818.77   150.8  820.18   160.9   824.8   170.9  829.57     181  833.84
   191.1  837.99   201.1  842.26   211.2   846.7   231.3  856.14   241.3  861.04
   271.5  876.11   291.6  886.35
#Mann= 3 , 0 , 0
       0      .1       0   135.8    .045       0   145.8      .1       0
Bank Sta=135.8,145.8
XS Rating Curve= 0 ,0
Exp/Cntr=0.3,0.1

Type RM Length L Ch R = 1 ,5369.9  ,295.7,292.1,288.6
XS GIS Cut Line= 2
     1595572.892      355964.013     1595820.589      355826.735
#Sta/Elev= 30
    10.1  841.73    20.2  840.12    30.3  838.41    40.5  836.65    50.6  834.81
    60.7  832.99    70.8  831.22    80.9  829.26      91  826.93   101.1  824.28
   111.3  820.93   121.4  817.23   126.5   816.2   131.5  815.18   136.5   815.2
   141.6  815.22   151.7  817.14   161.8  820.56   171.9  824.58   182.1  828.71
   192.2  833.35   202.3  838.16   212.4  843.37   222.5  848.67   232.6  854.15
   242.7  859.57   252.9  864.85     263  869.78   273.1  874.53   283.2  879.28
#Mann= 3 , 0 , 0
       0      .1       0   126.5    .045       0   136.5      .1       0
Bank Sta=126.5,136.5
XS Rating Curve= 0 ,0
Exp/Cntr=0.3,0.1

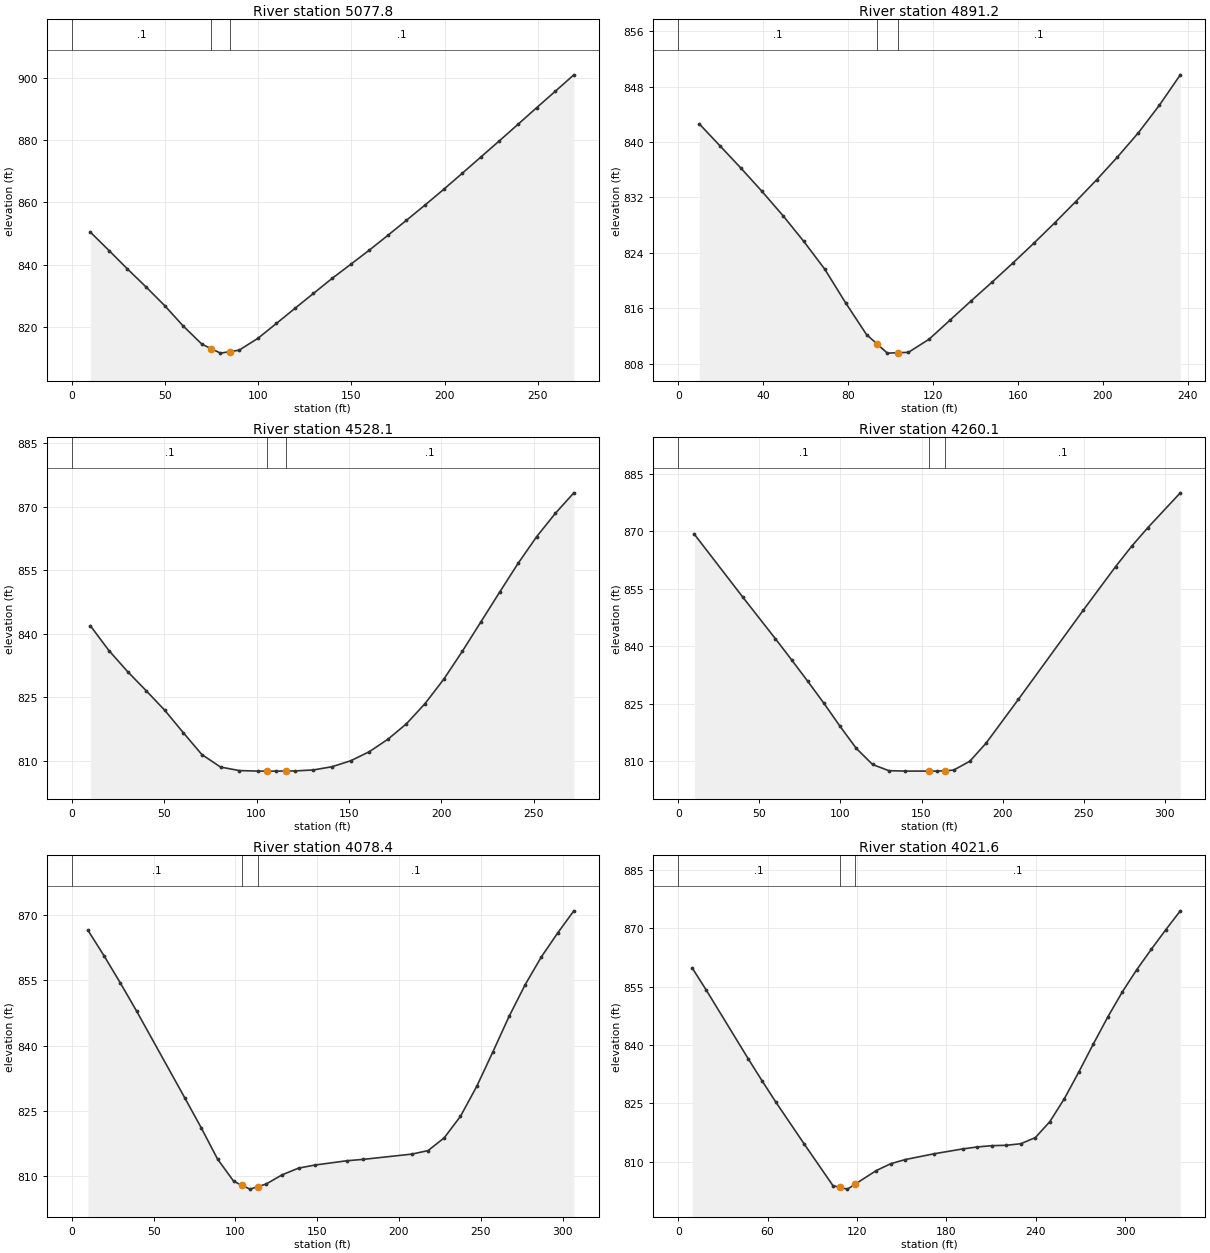
Type RM Length L Ch R = 1 ,5077.8  ,189.4,186.6,183.8
XS GIS Cut Line= 2
     1595781.224      356192.027     1595990.125      356021.922
#Sta/Elev= 29
      10  850.43      20  844.54    29.9  838.61    39.9  832.84    49.9  826.84
    59.9  820.27    69.8  814.52    74.8  813.07    79.8  811.63    84.8   812.1
    89.8  812.58    99.8  816.34   109.8  821.15   119.7  825.97   129.7  830.79
   139.7   835.6   149.7  840.13   159.6  844.65   169.6  849.41   179.6  854.26
   189.6  859.16   199.6  864.18   209.5  869.31   219.5  874.53   229.5  879.76
   239.5  885.06   249.4  890.34   259.4   895.6   269.4   900.9
#Mann= 3 , 0 , 0
       0      .1       0    74.8    .045       0    84.8      .1       0
Bank Sta=74.8,84.8
XS Rating Curve= 0 ,0
Exp/Cntr=0.3,0.1

Type RM Length L Ch R = 1 ,4891.2  ,358.2,363.1,366
XS GIS Cut Line= 2
     1595919.071      356334.065     1596080.223      356160.976
#Sta/Elev= 26
     9.9  842.64    19.7  839.45    29.6  836.22    39.4   832.9    49.3  829.39
    59.1  825.67      69  821.65    78.8   816.8    88.7  812.19    93.5  810.88
    98.5  809.51   103.5  809.57   108.4  809.62   118.2  811.53   128.1   814.3
     138  817.07   147.8  819.76   157.7  822.55   167.5  825.39   177.4  828.35
   187.2   831.4   197.1  834.56   206.9  837.85   216.8  841.37   226.6  845.31
   236.5  849.72
#Mann= 3 , 0 , 0
       0      .1       0    93.5    .045       0   103.5      .1       0
Bank Sta=93.5,103.5
XS Rating Curve= 0 ,0
Exp/Cntr=0.3,0.1

Type RM Length L Ch R = 1 ,4528.1  ,267.8,268,270.1
XS GIS Cut Line= 2
     1596130.956      356572.809     1596342.841      356402.704
#Sta/Elev= 29
    10.1  841.89    20.1  836.05    30.2  831.09    40.3  826.55    50.3  821.95
    60.4  816.62    70.4  811.48    80.5  808.53    90.6  807.69   100.6  807.57
   105.7  807.57   110.7  807.56   115.7  807.59   120.8  807.61   130.8  807.84
   140.9  808.61     151  810.02     161  812.15   171.1   815.1   181.1  818.74
   191.2  823.53   201.3  829.27   211.3  835.83   221.4  842.82   231.5  849.82
   241.5  856.63   251.6  862.97   261.7  868.47   271.7  873.31
#Mann= 3 , 0 , 0
       0      .1       0   105.7    .045       0   115.7      .1       0
Bank Sta=105.7,115.7
XS Rating Curve= 0 ,0
Exp/Cntr=0.3,0.1

Type RM Length L Ch R = 1 ,4260.1  ,183.4,181.8,180.1
XS GIS Cut Line= 2
      1596274.05      356774.838     1596534.989      356608.414
#Sta/Elev= 23
      10  869.18    39.9  852.75    59.9  841.95    69.9  836.43    79.9  830.81
    89.9  825.05    99.8  819.06   109.8  813.31   119.8  809.13   129.8  807.51
   139.8   807.4   154.7   807.4   159.7  807.39   164.7  807.52   169.7  807.65
   179.7  809.96   189.7  814.66   209.7  826.13   249.6  849.35   269.6  860.77
   279.5  866.08   289.5  870.95   309.5  880.03
#Mann= 3 , 0 , 0
       0      .1       0   154.7    .045       0   164.7      .1       0
Bank Sta=154.7,164.7
XS Rating Curve= 0 ,0
Exp/Cntr=0.3,0.1

Type RM Length L Ch R = 1 ,4078.4  ,67.1,56.8,46.5
XS GIS Cut Line= 2
     1596390.576      356918.802     1596633.836      356731.679
#Sta/Elev= 28
     9.9   866.5    19.8  860.61    29.7  854.41    39.6  847.98    69.3   827.9
    79.2  821.13    89.1  814.01      99  808.89   103.9     808   108.9   807.1
   113.9  807.69   118.8  808.27   128.7   810.4   138.6  811.92   148.5  812.62
   168.3  813.62   178.2  813.93   207.9  815.14   217.8  815.94   227.7  818.89
   237.6  823.82   247.5  830.66   257.4  838.59   267.3  846.74   277.2  854.06
   287.1  860.43     297  865.88   306.9  870.97
#Mann= 3 , 0 , 0
       0      .1       0   103.9    .045       0   113.9      .1       0
Bank Sta=103.9,113.9
XS Rating Curve= 0 ,0
Exp/Cntr=0.3,0.1

Type RM Length L Ch R = 1 ,4021.6  ,42.3,35.1,27.8
XS GIS Cut Line= 4
     1596422.541      356960.975     1596499.438      356925.944
     1596545.576      356819.142     1596663.485       356750.79
#Sta/Elev= 30
     9.4  859.79    18.8  854.12    46.9  836.53    56.3  830.81    65.7  825.25
    84.5  814.64   103.9  803.88   108.6  803.45   113.6     803   118.6  804.23
     133  807.78   142.7  809.53   152.4  810.59   171.8  812.08   191.1  813.33
   200.8  813.83   210.6  814.16   220.3  814.26     230  814.66   239.8  816.24
   249.5  820.33   259.3  826.27     269  833.11   278.7  840.27   288.5  847.27
   298.2  853.67   307.9  859.38   317.7  864.63   327.4  869.63   337.1  874.46
#Mann= 3 , 0 , 0
       0      .1       0   108.6    .045       0   118.6      .1       0
Bank Sta=108.6,118.6
XS Rating Curve= 0 ,0
Exp/Cntr=0.3,0.1

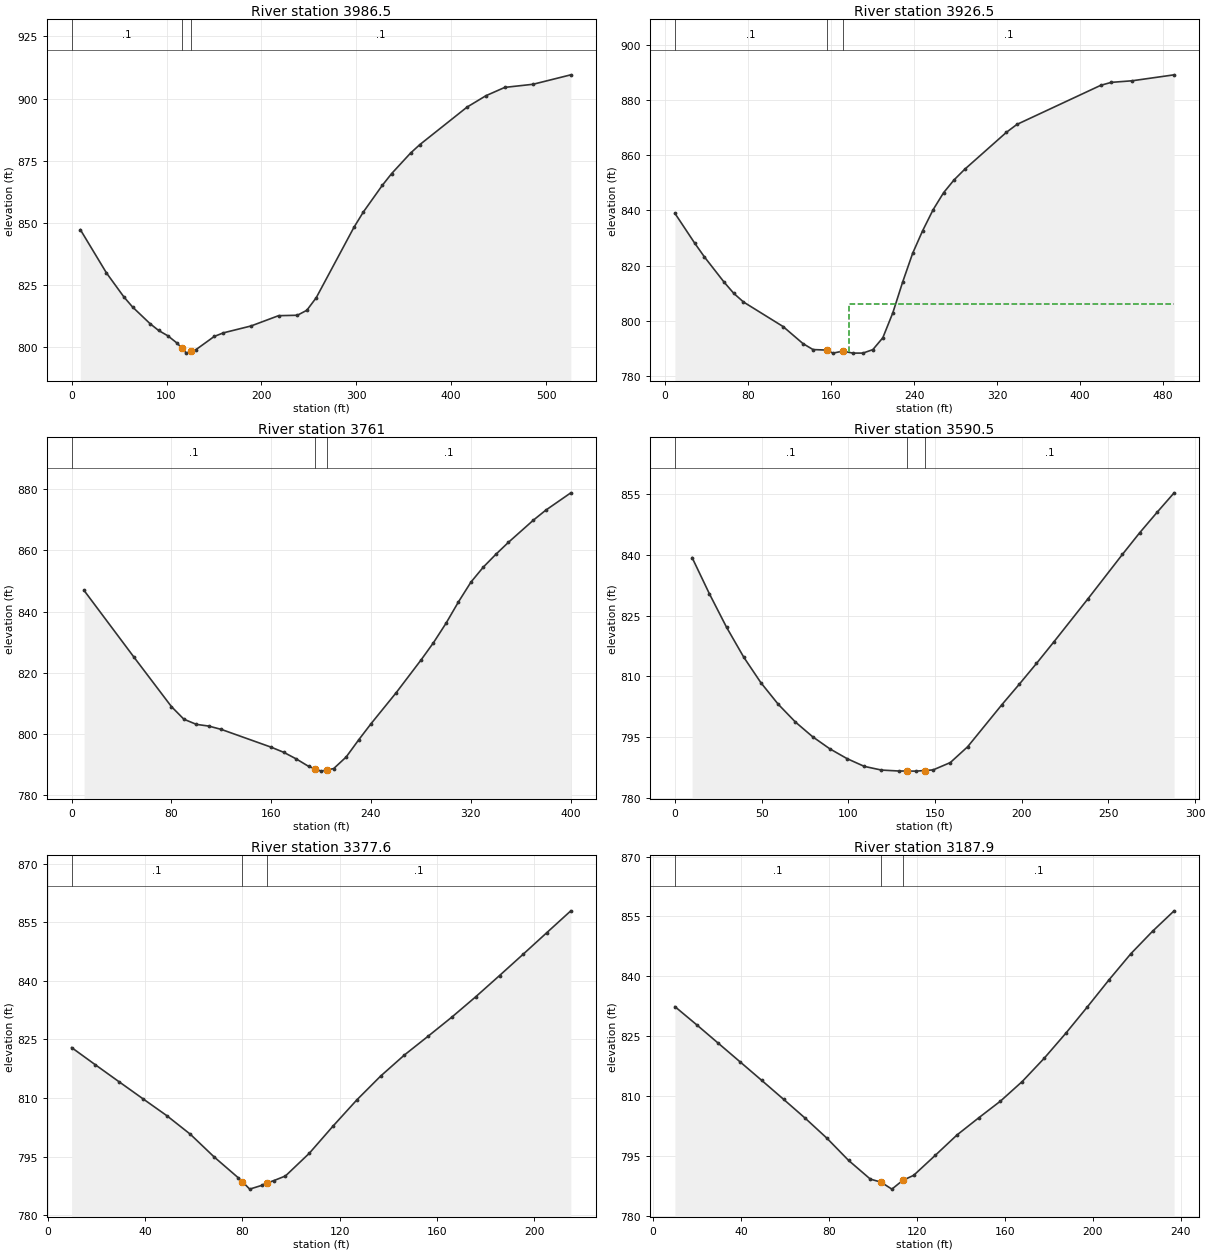
Type RM Length L Ch R = 1 ,3986.5  ,54,60,65.9
XS GIS Cut Line= 5
     1596460.124      356983.461     1596544.224      356946.896
      1596547.88      356868.891     1596561.287      356822.575
     1596828.211      356669.003
#Sta/Elev= 30
     9.2  847.23    36.7  829.82      55  820.19    64.2   816.1    82.5  809.44
    91.7  806.64   101.5  804.48   111.2  801.53     116  799.57     121  797.53
     126  798.21   130.7  798.85   150.3  804.25     160   805.7   189.1  808.47
     218   812.6   237.9  812.78   247.8  814.77   257.7  819.81   297.5  848.19
   307.4  854.35   327.3  865.04   337.2  869.81   357.1  878.05     367   881.5
   416.7  896.58   436.6  901.16   456.4   904.5   486.2  905.76     526  909.56
#Mann= 3 , 0 , 0
       0      .1       0     116    .045       0     126      .1       0
Bank Sta=116,126
XS Rating Curve= 0 ,0
Exp/Cntr=0.3,0.1

Type RM Length L Ch R = 1 ,3926.5  ,143.1,165.5,188.1
XS GIS Cut Line= 4
     1596500.346      357002.962     1596586.883      356965.178
     1596638.074      356820.138     1596848.931      356700.692
#Sta/Elev= 30
     9.4  838.97    28.3  828.28    37.8  823.22    56.7  814.12    66.1  810.03
    75.5  806.89   113.7     798   132.9  791.82   142.5  789.68  155.89  789.49
   161.7  788.39   171.3  789.11   180.9   788.4   190.6   788.4   200.2  789.66
   209.8  793.95   219.4  802.94     229   814.2   238.6  824.56   248.2   832.7
   258.3  840.29   268.4  846.45   278.5  851.08   288.6  854.86     329  868.31
   339.1  871.15   419.9   885.3     430  886.36   450.2  886.94   490.6  889.09
#Mann= 3 , 0 , 0
     9.4      .1       0  155.89    .045       0   171.3      .1       0
#XS Ineff= 2 , 0
                          177.15          805.99
Permanent Ineff=
       F       F
Bank Sta=155.89,171.3
XS Rating Curve= 0 ,0
Exp/Cntr=0.3,0.1

Type RM Length L Ch R = 1 ,3761    ,167.7,170.5,170.3
XS GIS Cut Line= 2
     1596501.749      357025.573     1596899.111      356978.242
#Sta/Elev= 30
      10  846.92      50  825.11      80  808.96      90  804.83     100  803.14
     110  802.58   120.1  801.48   160.1  795.66   170.1  793.99   180.1  791.84
   190.1  789.38   195.1  788.62   200.1  787.85   205.1  788.27   210.1  788.69
   220.1  792.47   230.1  798.06   240.1  803.39   260.1  813.45   280.1  824.19
   290.1  829.86   300.1  836.17   310.1  843.18   320.1  849.65   330.1  854.59
   340.1  858.75   350.1  862.64   370.2  869.93   380.2  873.21   400.2  878.86
#Mann= 3 , 0 , 0
       0      .1       0   195.1    .045       0   205.1      .1       0
Bank Sta=195.1,205.1
XS Rating Curve= 0 ,0
Exp/Cntr=0.3,0.1

Type RM Length L Ch R = 1 ,3590.5  ,208.6,212.8,220.1
XS GIS Cut Line= 2
     1596495.145      357121.336     1596782.434      357140.049
#Sta/Elev= 28
     9.9  839.26    19.9  830.33    29.8  822.09    39.7  814.74    49.6  808.45
    59.6  803.15    69.5  798.78    79.4  795.17    89.3   792.2    99.3  789.77
   109.2  787.87   119.1  786.96   129.1  786.73     134  786.72     139   786.7
     144  786.85   148.9     787   158.8   788.8   168.8  792.69   188.6  803.07
   198.6  808.09   208.5  813.19   218.4  818.43   238.3  829.16   258.1  840.05
     268  845.34     278  850.36   287.9  855.19
#Mann= 3 , 0 , 0
       0      .1       0     134    .045       0     144      .1       0
Bank Sta=134,144
XS Rating Curve= 0 ,0
Exp/Cntr=0.3,0.1

Type RM Length L Ch R = 1 ,3377.6  ,193,189.7,186.4
XS GIS Cut Line= 2
     1596507.253      357312.863     1596714.189      357371.201
#Sta/Elev= 26
     9.8  822.92    19.5  818.54    29.3  814.17    39.1  809.82    48.9   805.5
    58.6  800.73    68.4  794.91    78.2  789.64   80.01  788.58      83  786.68
      88  787.65   90.01  788.23      93  788.88    97.7  790.05   107.5  795.86
   117.3  802.85     127   809.5   136.8  815.61   146.6  821.02   156.4  825.86
   166.1  830.72   175.9  835.92   185.7  841.36   195.5  846.87   205.2  852.38
     215  857.93
#Mann= 3 , 0 , 0
     9.8      .1       0   80.01    .045       0   90.01      .1       0
Bank Sta=80.01,90.01
XS Rating Curve= 0 ,0
Exp/Cntr=0.3,0.1

Type RM Length L Ch R = 1 ,3187.9  ,158.9,168.3,177.7
XS GIS Cut Line= 2
     1596433.447      357506.293     1596669.071      357532.092
#Sta/Elev= 26
     9.9   832.4    19.8  827.85    29.6  823.24    39.5  818.58    49.4  813.91
    59.3  809.19    69.1  804.47      79  799.45    88.9  793.86    98.8  789.17
   103.6  788.42   108.6  786.66   113.6  788.88   118.5  790.11   128.4  795.16
   138.3  800.27   148.1  804.53     158  808.72   167.9  813.63   177.8   819.4
   187.7  825.71   197.5  832.31   207.4  839.13   217.3  845.65   227.2   851.3
     237  856.41
#Mann= 3 , 0 , 0
     9.9      .1       0   103.6    .045       0   113.6      .1       0
Bank Sta=103.6,113.6
XS Rating Curve= 0 ,0
Exp/Cntr=0.3,0.1

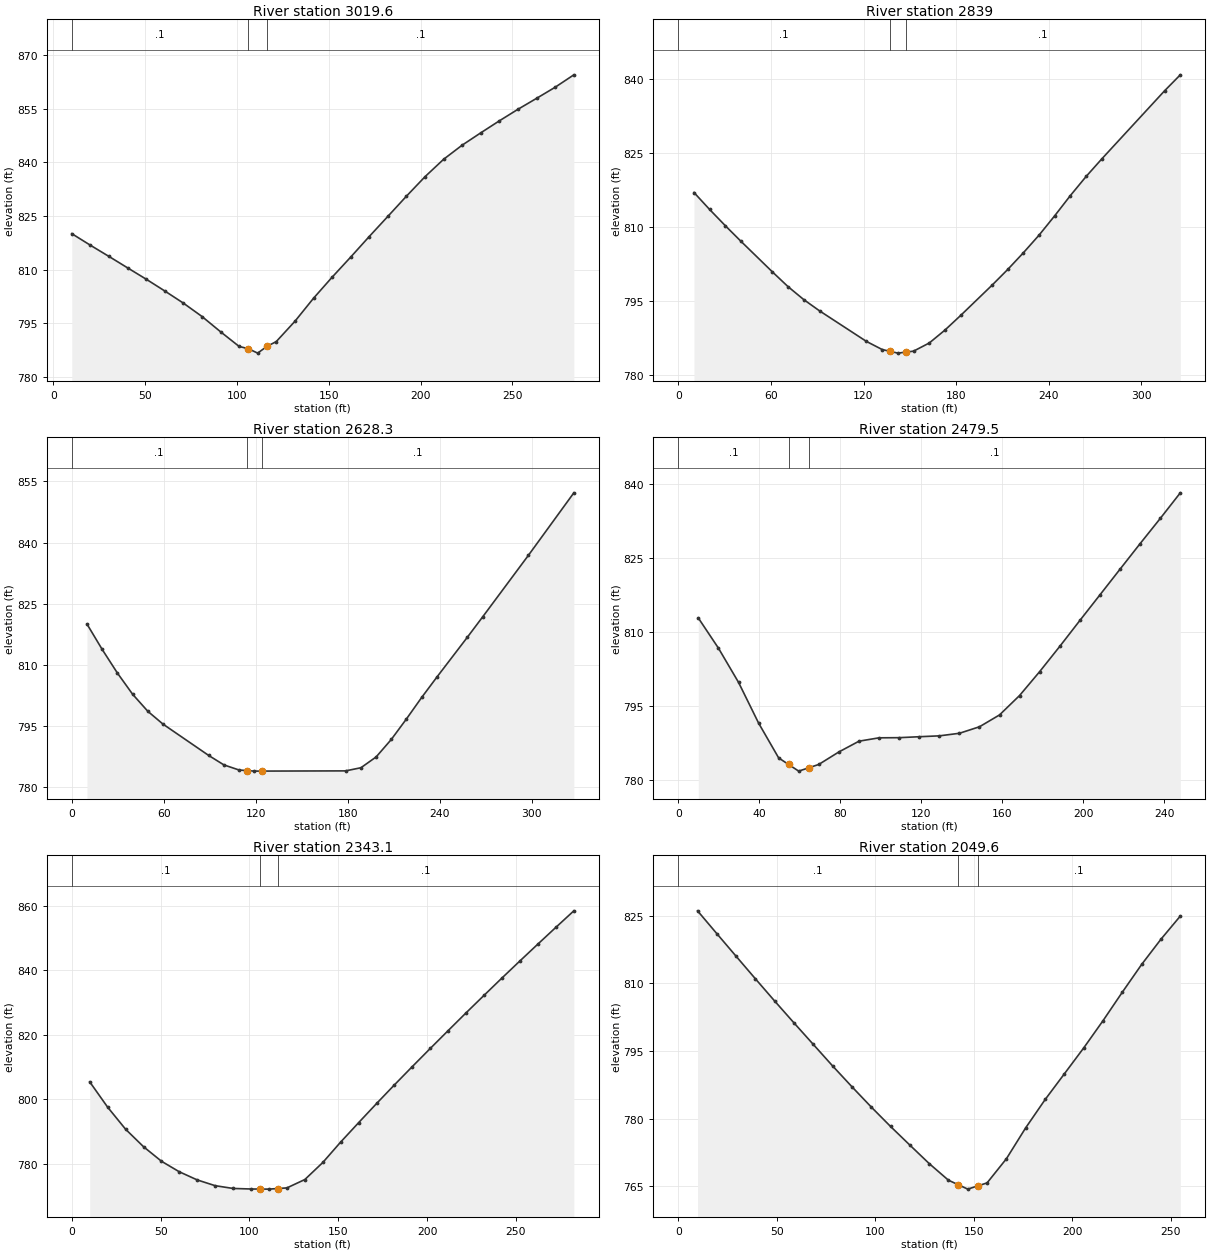
Type RM Length L Ch R = 1 ,3019.6  ,190.3,180.6,170.9
XS GIS Cut Line= 2
     1596409.219      357620.619     1596646.563      357775.409
#Sta/Elev= 30
    10.1  820.05    20.2  816.82    30.4  813.66    40.5  810.48    50.6  807.32
    60.7  804.03    70.8  800.64      81  796.88    91.1  792.61   101.2  788.51
   106.3  787.86   111.3  786.64   116.3  788.52   121.4  789.86   131.6  795.56
   141.7  801.99   151.8  807.86   161.9  813.48     172  819.23   182.2   824.9
   192.3  830.54   202.4  835.98   212.5  840.84   222.6  844.79   232.8  848.26
   242.9  851.61     253  854.83   263.1  857.88   273.2  860.98   283.4  864.46
#Mann= 3 , 0 , 0
    10.1      .1       0   106.3    .045       0   116.3      .1       0
Bank Sta=106.3,116.3
XS Rating Curve= 0 ,0
Exp/Cntr=0.3,0.1

Type RM Length L Ch R = 1 ,2839    ,213.9,210.7,207.6
XS GIS Cut Line= 2
     1596221.752      357796.047      1596545.09      357830.445
#Sta/Elev= 27
    10.2  817.01    20.3  813.57    30.5  810.26    40.6   807.1      61  800.87
    71.1  797.88    81.3  795.24    91.5  792.96   121.9  786.74   132.1  785.09
   137.3  784.72   142.3  784.36   147.3  784.56   152.4  784.76   162.6  786.42
   172.7  789.03   182.9  792.01   203.2  798.15   213.4  801.36   223.5  804.74
   233.7  808.34   243.9   812.3     254  816.39   264.2  820.27   274.4  823.86
     315  837.68   325.2  840.93
#Mann= 3 , 0 , 0
       0      .1       0   137.3    .045       0   147.3      .1       0
Bank Sta=137.3,147.3
XS Rating Curve= 0 ,0
Exp/Cntr=0.3,0.1

Type RM Length L Ch R = 1 ,2628.3  ,156.9,148.8,140
XS GIS Cut Line= 2
     1596205.626      358026.323     1596532.462      358008.656
#Sta/Elev= 23
     9.9  820.03    19.8  813.82    29.8  807.99    39.7  802.81    49.6  798.64
    59.5   795.5    89.3  787.82    99.2  785.51   109.1  784.26     114  784.13
     119  783.99     124     784   178.5  784.05   188.5  784.82   198.4  787.46
   208.3  791.75   218.2  796.79   228.1  802.04     238  807.02   257.9   816.8
   267.8  821.75   297.6  836.82   327.3  852.17
#Mann= 3 , 0 , 0
       0      .1       0     114    .045       0     124      .1       0
Bank Sta=114,124
XS Rating Curve= 0 ,0
Exp/Cntr=0.3,0.1

Type RM Length L Ch R = 1 ,2479.5  ,136.9,136.4,136.6
XS GIS Cut Line= 2
      1596280.71      358185.324     1596508.065      358086.299
#Sta/Elev= 27
     9.9  812.77    19.8  806.68    29.8   799.7    39.7  791.45    49.6   784.4
    54.5  783.07    59.5  781.72    64.5   782.4    69.4  783.07    79.4  785.62
    89.3  787.79    99.2  788.47   109.1   788.5     119  788.69     129  788.87
   138.9  789.39   148.8  790.71   158.7  793.11   168.6  797.04   178.5  801.87
   188.5  807.02   198.4  812.26   208.3  817.44   218.2  822.63   228.1   827.8
   238.1  832.93     248  838.12
#Mann= 3 , 0 , 0
       0      .1       0    54.5    .045       0    64.5      .1       0
Bank Sta=54.5,64.5
XS Rating Curve= 0 ,0
Exp/Cntr=0.3,0.1

Type RM Length L Ch R = 1 ,2343.1  ,281.6,293.5,305.4
XS GIS Cut Line= 2
     1596317.105      358310.355     1596573.274      358191.104
#Sta/Elev= 30
    10.1  805.36    20.2  797.49    30.3  790.65    40.4  785.22    50.5  780.71
    60.5  777.45    70.6  774.92    80.7  773.13    90.8  772.27   100.9   772.1
     106  772.08     111  772.06     116  772.25   121.1  772.44   131.2  775.04
   141.3  780.33   151.4   786.7   161.5  792.71   171.6  798.65   181.6  804.41
   191.7  810.11   201.8  815.73   211.9  821.29     222  826.81   232.1  832.23
   242.2  837.62   252.3  842.91   262.4  848.14   272.5  853.32   282.6  858.44
#Mann= 3 , 0 , 0
       0      .1       0     106    .045       0     116      .1       0
Bank Sta=106,116
XS Rating Curve= 0 ,0
Exp/Cntr=0.3,0.1

Type RM Length L Ch R = 1 ,2049.6  ,126.5,134.6,142.8
XS GIS Cut Line= 2
     1596338.127       358512.16     1596589.879       358551.91
#Sta/Elev= 28
     9.8  826.05    19.6  820.99    29.4  815.97    39.2  810.97      49  806.03
    58.8  801.19    68.6  796.42    78.4  791.65    88.2  787.04      98  782.55
   107.8  778.24   117.6  774.11   127.4  770.02   137.2  766.32     142  765.36
     147  764.35     152  765.06   156.8  765.73   166.6  771.08   176.4  777.94
   186.3  784.23   196.1  789.95   205.9  795.68   215.7  801.72   225.5  808.04
   235.3  814.18   245.1  819.77   254.9  824.89
#Mann= 3 , 0 , 0
       0      .1       0     142    .045       0     152      .1       0
Bank Sta=142,152
XS Rating Curve= 0 ,0
Exp/Cntr=0.3,0.1

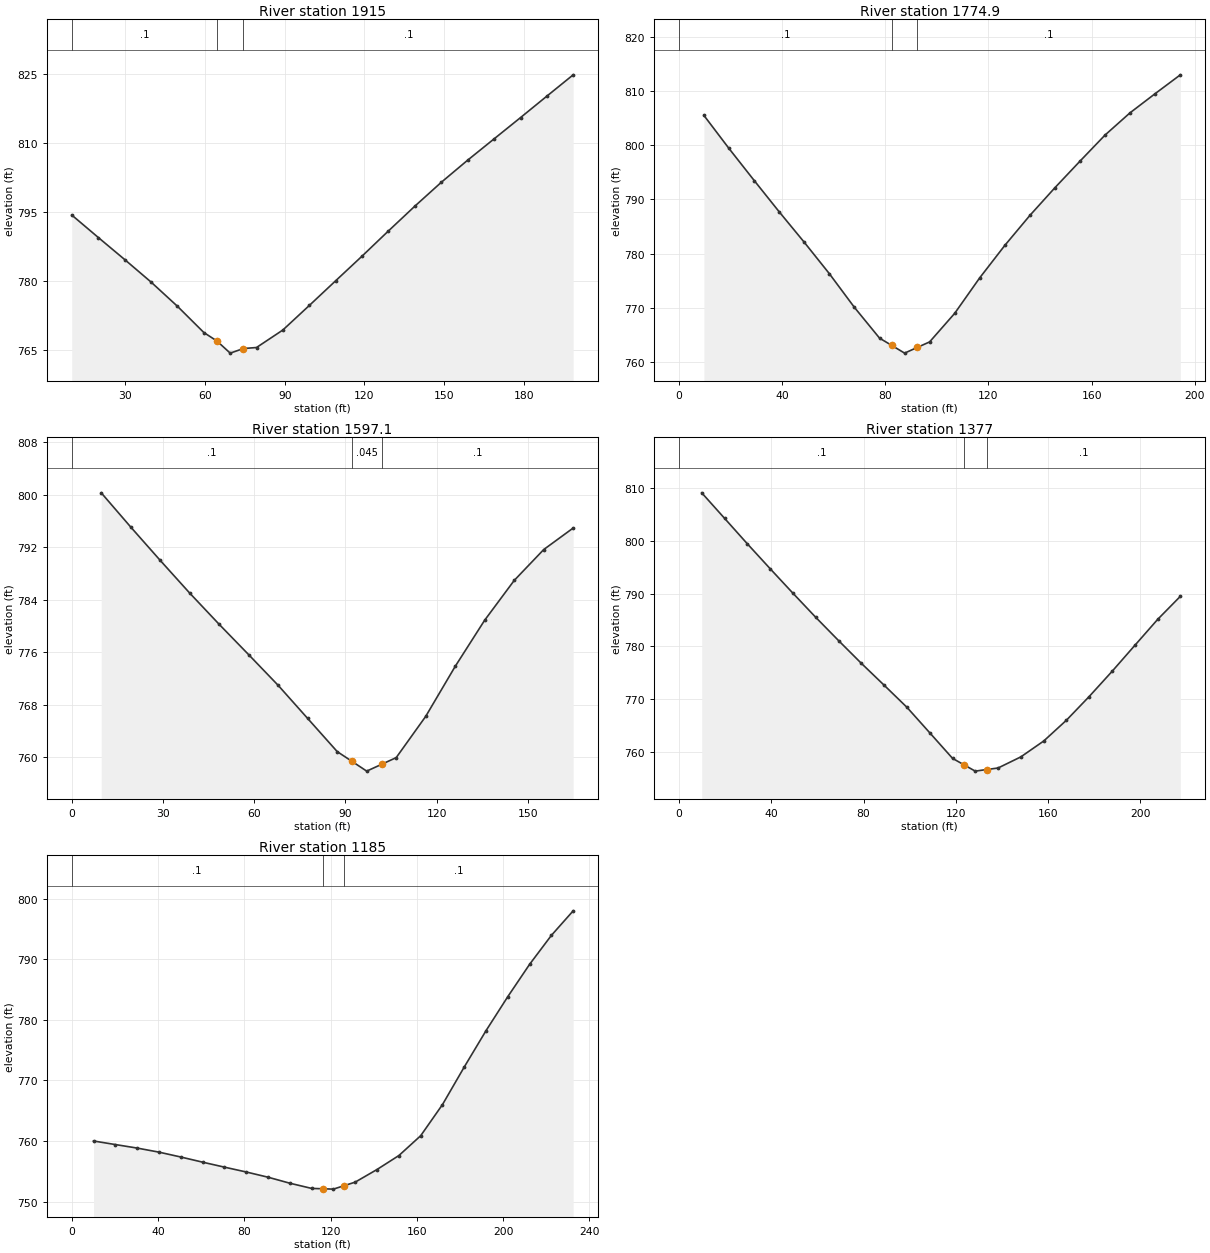
Type RM Length L Ch R = 1 ,1915    ,144,140.1,136.2
XS GIS Cut Line= 2
     1596373.461      358618.161     1596541.295      358724.162
#Sta/Elev= 22
     9.9  794.34    19.9  789.45    29.8  784.67    39.7  779.79    49.6  774.54
    59.6   768.8    64.5  766.97    69.5  764.33    74.5  765.33    79.4  765.55
    89.3  769.35    99.3  774.71   109.2  780.07   119.1  785.41     129  790.87
     139  796.29   148.9  801.45   158.8  806.25   168.7  810.86   178.7  815.51
   188.6  820.17   198.5   824.8
#Mann= 3 , 0 , 0
     9.9      .1       0    64.5    .045       0    74.5      .1       0
Bank Sta=64.5,74.5
XS Rating Curve= 0 ,0
Exp/Cntr=0.3,0.1

Type RM Length L Ch R = 1 ,1774.9  ,178.1,177.8,177.5
XS GIS Cut Line= 2
      1596280.71      358746.245     1596461.795      358816.912
#Sta/Elev= 22
     9.7   805.5    19.4  799.41    29.2  793.48    38.9   787.7    48.6  782.09
    58.3  776.31      68   770.1    77.8  764.39    82.5  763.06    87.5  761.63
    92.5   762.7    97.2   763.7   106.9  768.96   116.6  775.51   126.4  781.54
   136.1  787.06   145.8  792.17   155.5  797.06   165.2  801.87   174.9  805.98
   184.7  809.54   194.4  812.99
#Mann= 3 , 0 , 0
       0      .1       0    82.5    .045       0    92.5      .1       0
Bank Sta=82.5,92.5
XS Rating Curve= 0 ,0
Exp/Cntr=0.3,0.1

Type RM Length L Ch R = 1 ,1597.1  ,220.3,220.1,219.9
XS GIS Cut Line= 2
     1596218.876      358909.663     1596373.461       358967.08
#Sta/Elev= 19
     9.7   800.3    19.4  795.08    29.1  789.99    38.8     785    48.5  780.23
    58.2   775.6    67.9  770.92    77.6  765.87    87.3  760.82      92  759.38
      97  757.84     102   758.9   106.7   759.9   116.4  766.19   126.1  773.82
   135.8  780.87   145.5  786.93   155.2  791.64   164.9  794.93
#Mann= 3 , 0 , 0
       0      .1       0      92    .045       0     102      .1       0
Bank Sta=92,102
XS Rating Curve= 0 ,0
Exp/Cntr=0.3,0.1

Type RM Length L Ch R = 1 ,1377    ,198.9,192,185.1
XS GIS Cut Line= 2
     1596098.052      359100.564     1596302.618      359173.998
#Sta/Elev= 24
     9.9  809.07    19.8  804.24    29.6  799.45    39.5  794.73    49.4  790.08
    59.3  785.51    69.2   781.1      79  776.83    88.9  772.68    98.8  768.49
   108.7  763.66   118.6  758.81   123.4  757.63   128.4   756.4   133.4   756.7
   138.3  756.99   148.2   759.1   158.1   762.1   167.9  766.02   177.8  770.52
   187.7  775.27   197.6  780.21   207.5  785.13   217.3  789.48
#Mann= 3 , 0 , 0
       0      .1       0   123.4    .045       0   133.4      .1       0
Bank Sta=123.4,133.4
XS Rating Curve= 0 ,0
Exp/Cntr=0.3,0.1

Type RM Length L Ch R = 1 ,1185    ,1166.9,1185,1203.2
XS GIS Cut Line= 2
     1596042.103      359329.608     1596274.643      359329.608
#Sta/Elev= 25
    10.1  760.01    20.2  759.42    30.3  758.84    40.4  758.17    50.6  757.36
    60.7  756.51    70.8  755.69    80.9  754.89      91  754.03   101.1  753.04
   111.2  752.18   116.3  752.12   121.3  752.06   126.3  752.63   131.4  753.21
   141.5  755.29   151.7  757.61   161.8  760.88   171.9  766.02     182  772.23
   192.1  778.23   202.2  783.85   212.3  789.18   222.4  793.96   232.5  798.01
#Mann= 3 , 0 , 0
       0      .1       0   116.3    .045       0   126.3      .1       0
Bank Sta=116.3,126.3
XS Rating Curve= 0 ,0
Exp/Cntr=0.3,0.1

Chan Stop Cuts=-1
Use User Specified Reach Order=0